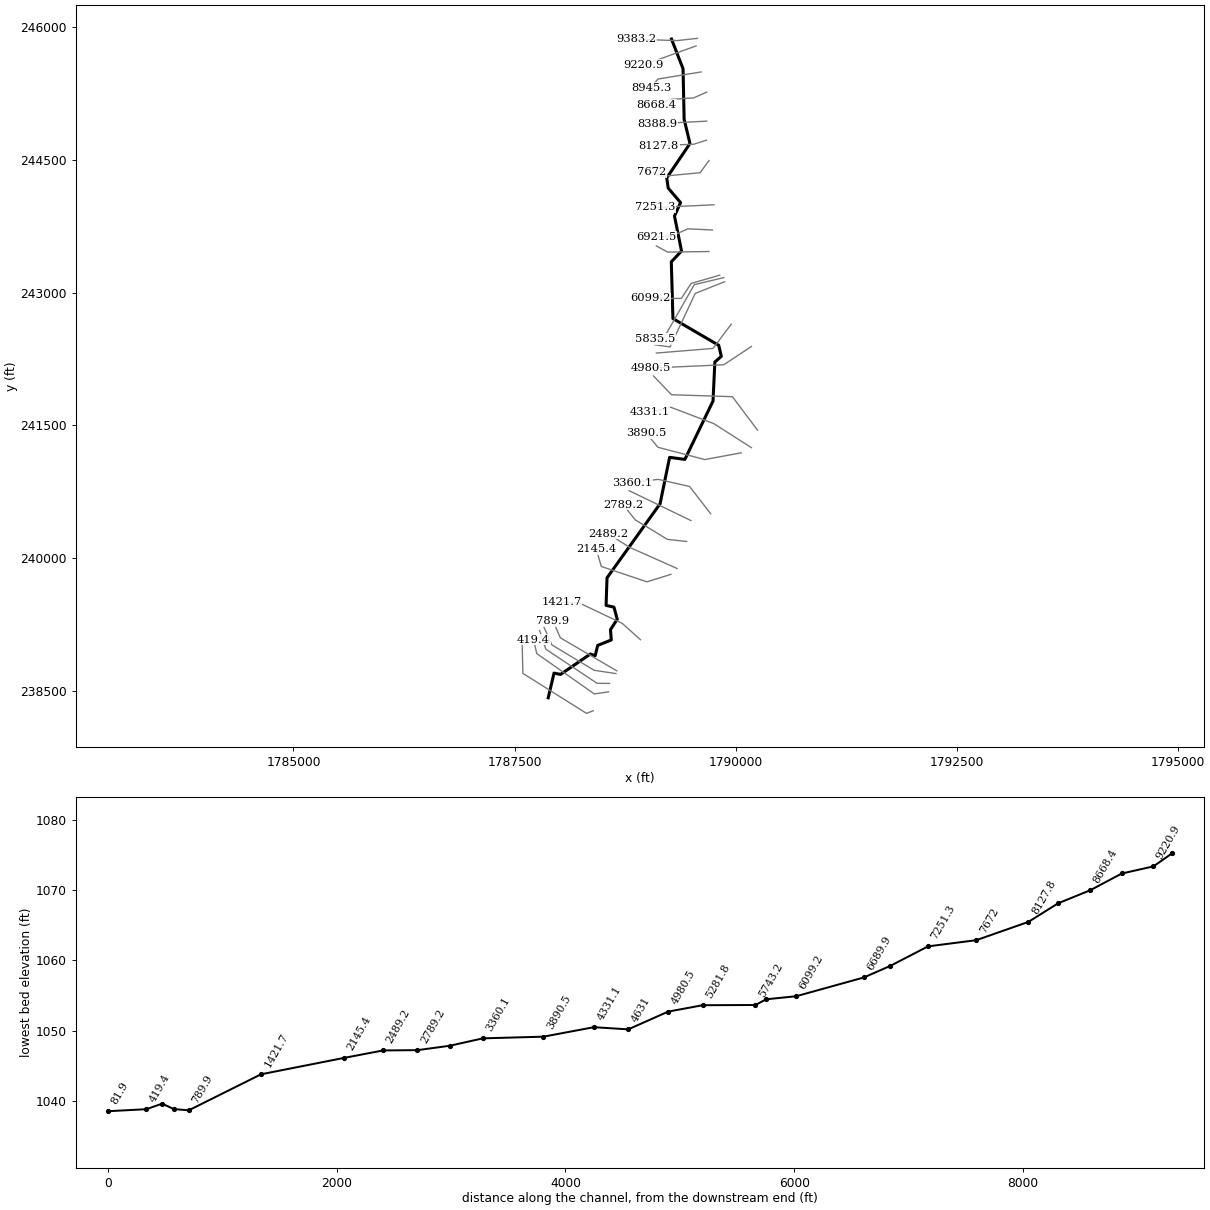
--- STEWARTRN.prj (project) ---

Proj Title=STEWARTRN
Current Plan=p01
Default Exp/Contr=0,0
English Units
Geom File=g01
Flow File=f01
Plan File=p01
BEGIN DESCRIPTION:
END DESCRIPTION:
DSS Export Rating Curves= 0
DSS Export Rating Curve Sorted= 0
DSS Export Volume Flow Curves= 0
DXF OffsetX= 0
DXF OffsetY= 0
DXF ScaleX= 0
DXF ScaleY= 0

--- STEWARTRN.p01 (plan) ---

Plan Title=Floodplain
Program Version=4.00
Geom File=g01
Flow File=f01
K Sum by GR=0
Std Step Tol=0.01
Critical Tol=0.01
Num of Std Step Trials=20
Max Error Tol=0.3
Flow Tol Ratio=0.001
Split Flow NTrial=30
Split Flow Tol=0.02
Split Flow Ratio=0.02
Log Output Level=0
Friction Slope Method=1
Unsteady Friction Slope Method=2
Unsteady Bridges Friction Slope Method=1
Global Log Level=0
CheckData=False
Run HTab=0
Run UNet=0
Run PostProcess=0
UNET Theta=0
UNET Theta Warmup=0
UNET ZTol=0
UNET ZSATol=0
UNET MxIter=0
UNET MaxInSteps=0
UNET DtIC=0
UNET DtMin=0
UNET MaxCRTS=0
UNET WFStab=0
UNET SFStab=0
UNET WFX=0
UNET SFX=0
UNET DSS MLevel=0
UNET DZMax Abort=0
UNET Convert EG Bridges=0
UNET Use Existing IB Tables=0
UNET Froude Limit=0
UNET Froude Power=0
Write IC File=0
Echo Input=False
Echo Output=False
Write Detailed=0

--- STEWARTRN.f01 (steady flow) ---

Flow Title=NFF Regression Equation
Program Version=5.03
Number of Profiles= 1
Profile Names=P100yr
River Rch & RM=STEWARTRN,Main            ,9383.2
887.6996
River Rch & RM=STEWARTRN,Main            ,7672
933.0504
River Rch & RM=STEWARTRN,Main            ,7251.3
1263.646
River Rch & RM=STEWARTRN,Main            ,4631
1300.943
River Rch & RM=STEWARTRN,Main            ,3890.5
1468.116
River Rch & RM=STEWARTRN,Main            ,1421.7
1512.754
River Rch & RM=STEWARTRN,Main            ,81.9
1605.922
Boundary for River Rch & Prof#=STEWARTRN,Main            , 1
Up Type= 0
Dn Type= 3
Dn Slope=0.00087
DSS Import GetInterval= 0
DSS Import GetPeak= 0
DSS Import FillOption= 0

--- STEWARTRN.g01 (geometry) ---

Geom Title=USGS 10m DEM
Program Version=4.10

River Reach=STEWARTRN       ,Main
Reach XY= 30
     1789272.264       245861.09     1789402.909      245525.242
     1789415.168      244954.856     1789481.284      244681.845
     1789218.772      244294.032     1789234.755      244179.011
     1789374.742      244015.079     1789306.119      243862.754
      1789385.79      243468.445     1789270.209       243346.51
     1789288.474      242705.914     1789806.179      242404.302
     1789835.439       242278.65     1789762.525       242216.24
     1789741.681      241775.258     1789423.499      241116.328
     1789250.901      241139.823     1789143.313      240615.607
     1788543.584       239779.47     1788532.936      239468.368
     1788621.802      239449.243     1788659.052       239312.41
     1788582.881       239195.24     1788591.639      239078.183
     1788438.302      239017.083     1788409.848      238901.423
     1788355.613      238919.733     1788018.446      238689.522
     1787944.487      238704.183     1787879.175      238425.436

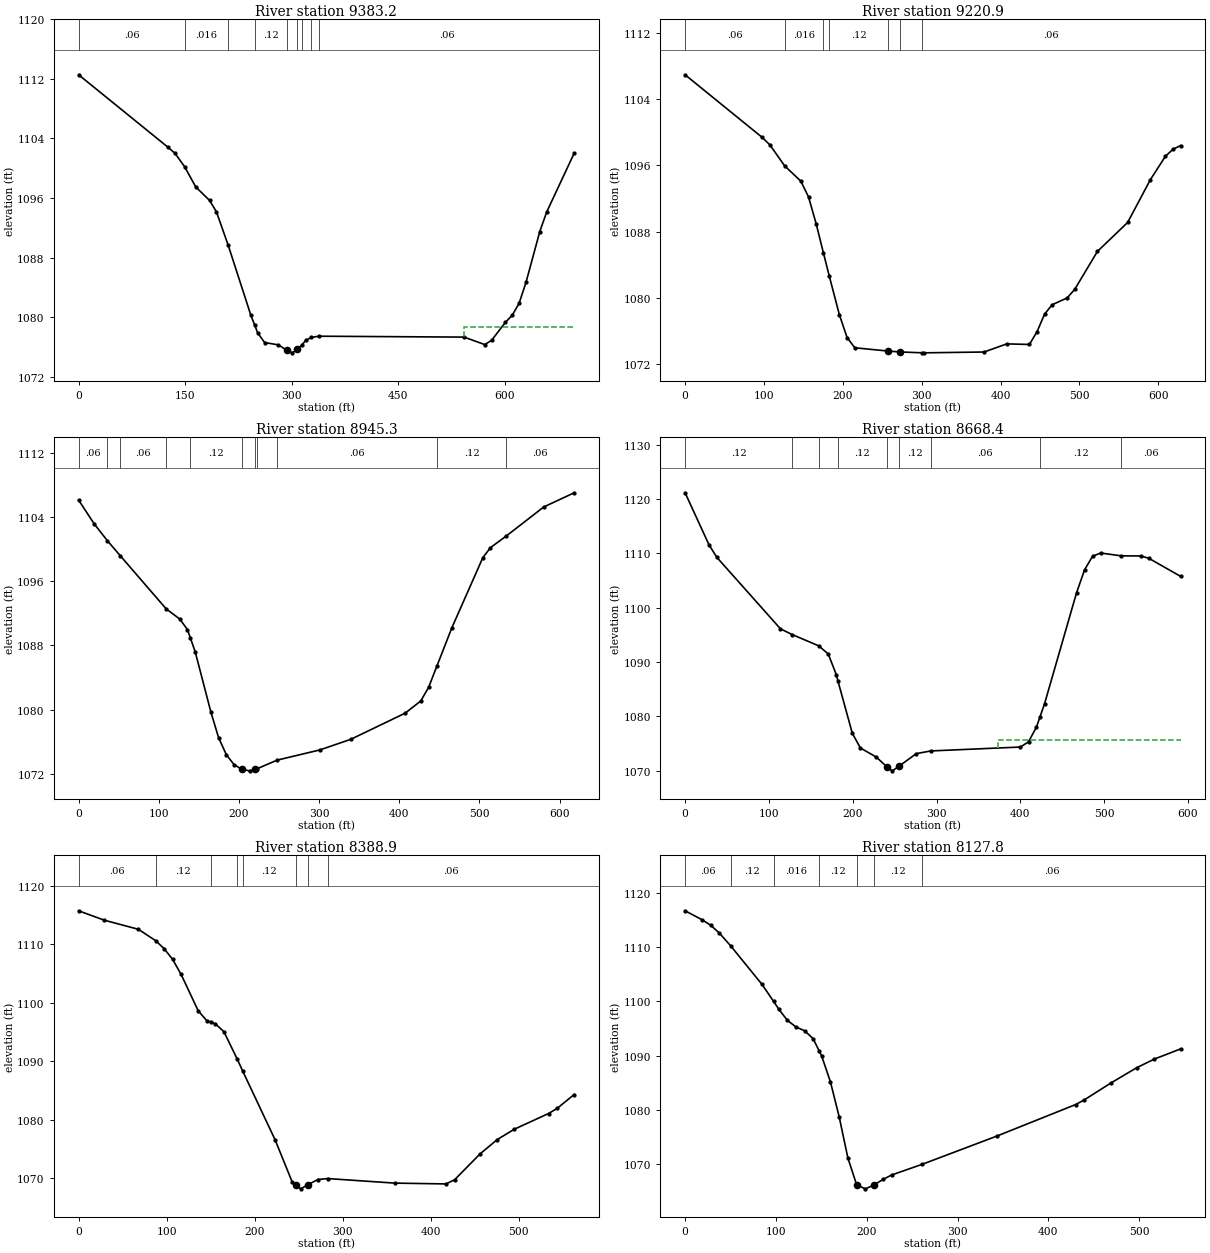
Type RM Length L Ch R = 1 ,9383.2  ,154.2,162.2,170.2
XS GIS Cut Line= 3
      1789566.88      245868.969     1789335.568      245843.367
     1788871.159      245858.558
#Sta/Elev= 30
       0 1112.55   126.1  1102.8   135.8 1101.99  149.08 1100.23   164.8  1097.5
   184.2  1095.7   193.9 1094.17   210.61089.648   242.4 1080.28  247.511079.021
   252.1 1077.89   261.8 1076.62   281.1 1076.31   292.6 1075.61   300.5 1075.24
   307.6 1075.69   313.7 1076.25   319.8 1076.93  327.681077.312  338.171077.471
   542.5 1077.35   571.5 1076.35   581.2 1076.92   600.6 1079.33   610.3 1080.29
   619.9 1081.89   629.6 1084.69     649 1091.51   658.7 1094.13   697.4 1102.03
#Mann= 9 ,-1 , 0
       0     .06       0  149.08    .016       0   210.6     .06       0
  247.51     .12       0   292.6    .045       0   307.6     .12       0
   313.7     .06       0  327.68     .12       0  338.17     .06       0
#XS Ineff= 2 , 0
                           541.8         1078.65
Permanent Ineff=
       F       F
Bank Sta=292.6,307.6
XS Rating Curve= 0 ,0
Exp/Cntr=0.3,0.1

Type RM Length L Ch R = 1 ,9220.9  ,278.4,275.7,270.1
XS GIS Cut Line= 3
     1789550.127      245783.106     1789301.448      245694.131
     1788959.399      245568.961
#Sta/Elev= 30
       0 1106.94    97.8 1099.38   107.6 1098.47  126.211095.953   146.7 1094.11
   156.5 1092.21   166.3 1088.93   175.31085.486   182.81082.664   195.6    1078
   205.4 1075.24   215.2    1074   256.9 1073.61   271.9  1073.5   299.81073.398
   302.5 1073.39   379.1 1073.49   407.9 1074.47   436.6  1074.4   446.2 1075.92
   455.8 1078.05   465.4 1079.19   484.6 1080.02   494.2 1081.07   522.9 1085.63
   561.2 1089.12     590 1094.28   609.2 1097.12   618.8 1097.96   628.4  1098.4
#Mann= 7 ,-1 , 0
       0     .06       0  126.21    .016       0   175.3     .06       0
   182.8     .12       0   256.9    .045       0   271.9     .12       0
   299.8     .06       0
Bank Sta=256.9,271.9
XS Rating Curve= 0 ,0
Exp/Cntr=0.3,0.1

Type RM Length L Ch R = 1 ,8945.3  ,280.2,276.8,273.9
XS GIS Cut Line= 3
     1789606.836      245489.634     1789118.555      245409.339
      1789040.43      245313.853
#Sta/Elev= 30
       0  1106.1    19.4 1103.14   35.811101.051   51.981099.165  109.231092.551
   126.1 1091.29   135.8 1089.97  139.251088.978   145.5 1087.18     165  1079.7
   174.6 1076.51   184.4 1074.36     194 1073.15   203.8 1072.56   213.5 1072.38
  219.88 1072.55   222.8 1072.65  247.781073.719   300.8 1074.98   339.6 1076.31
   407.5 1079.57   426.9 1081.09   436.6 1082.78  447.01 1085.44   465.7 1090.22
   504.3 1098.94   513.8 1100.18  533.671101.639   580.2 1105.24   618.2 1107.01
#Mann= 11 ,-1 , 0
       0     .06       0   35.81     .12       0   51.98     .06       0
  109.23    .016       0  139.25     .12       0   203.8    .045       0
  219.88    .045       0   222.8     .12       0  247.78     .06       0
  447.01     .12       0  533.67     .06       0
Bank Sta=203.8,219.88
XS Rating Curve= 0 ,0
Exp/Cntr=0.3,0.1

Type RM Length L Ch R = 1 ,8668.4  ,279.9,279.5,278.8
XS GIS Cut Line= 4
      1789669.77       245261.77       1789522.2      245196.665
     1789255.273      245179.304     1789105.534       245116.37
#Sta/Elev= 30
       0 1121.14    28.5 1111.57      38 1109.24   113.8 1096.11  127.641095.066
  159.291092.992   170.8 1091.49   180.4 1087.67  182.341086.526   199.5  1076.9
   209.1  1074.2   228.2 1072.51   240.7 1070.73   247.3 1069.99   255.7  1070.9
   275.9 1073.16  293.051073.649   400.1 1074.37   409.7 1075.33   419.2 1078.04
  423.371079.895   428.8 1082.31     467 1102.73   476.6 1106.97   486.1 1109.46
   495.7 1110.06  520.461109.536   543.4 1109.52     553 1109.11   591.2 1105.76
#Mann= 9 ,-1 , 0
       0     .12       0  127.64     .06       0  159.29    .016       0
  182.34     .12       0   240.7    .045       0   255.7     .12       0
  293.05     .06       0  423.37     .12       0  520.46     .06       0
#XS Ineff= 2 , 0
                          372.76         1075.61
Permanent Ineff=
       F       F
Bank Sta=240.7,255.7
XS Rating Curve= 0 ,0
Exp/Cntr=0.3,0.1

Type RM Length L Ch R = 1 ,8388.9  ,261.2,261.1,261.3
XS GIS Cut Line= 2
      1789669.77      244934.079     1789107.704      244905.867
#Sta/Elev= 30
       0 1115.72    29.1 1114.11    67.9 1112.55   87.471110.606      97 1109.26
   106.7 1107.41   116.4 1104.83   135.8 1098.61   145.5 1096.92  150.431096.651
   155.2 1096.39     165 1095.03  180.03 1090.37  186.561088.222   223.2 1076.51
   242.6 1069.29  246.71 1068.78   252.3 1068.14  260.02 1068.82   271.7 1069.73
  282.79  1069.9     359 1069.12   417.2 1068.98   426.9 1069.68     456 1074.13
   475.4 1076.57   494.8 1078.34   533.7 1081.03   543.4  1081.9   562.8 1084.28
#Mann= 8 ,-1 , 0
       0     .06       0   87.47     .12       0  150.43    .016       0
  180.03     .06       0  186.56     .12       0  246.71    .045       0
  260.02     .12       0  282.79     .06       0
Bank Sta=246.71,260.02
XS Rating Curve= 0 ,0
Exp/Cntr=0.3,0.1

Type RM Length L Ch R = 1 ,8127.8  ,453.6,455.8,456.3
XS GIS Cut Line= 3
       1789667.6      244719.235     1789524.371      244673.662
     1789129.405      244658.471
#Sta/Elev= 30
       0 1116.66    18.8    1115    28.2 1113.99    37.6 1112.58    50.31110.183
    84.6 1103.12   97.51 1099.97   103.3 1098.51   112.7 1096.48   122.1 1095.27
   131.5 1094.58   140.9 1093.14  147.58 1090.88   150.3 1089.96     160 1085.18
   169.6 1078.77   179.2 1071.18   188.9 1066.21   198.5 1065.48   208.2 1066.21
   217.8  1067.2   227.4 1068.03  261.12    1070   343.1 1075.18   429.9 1080.99
   439.5 1081.85   468.4 1084.92   497.4 1087.79   516.6 1089.36   545.6 1091.24
#Mann= 7 ,-1 , 0
       0     .06       0    50.3     .12       0   97.51    .016       0
  147.58     .12       0   188.9    .045       0   208.2     .12       0
  261.12     .06       0
Bank Sta=188.9,208.2
XS Rating Curve= 0 ,0
Exp/Cntr=0.3,0.1

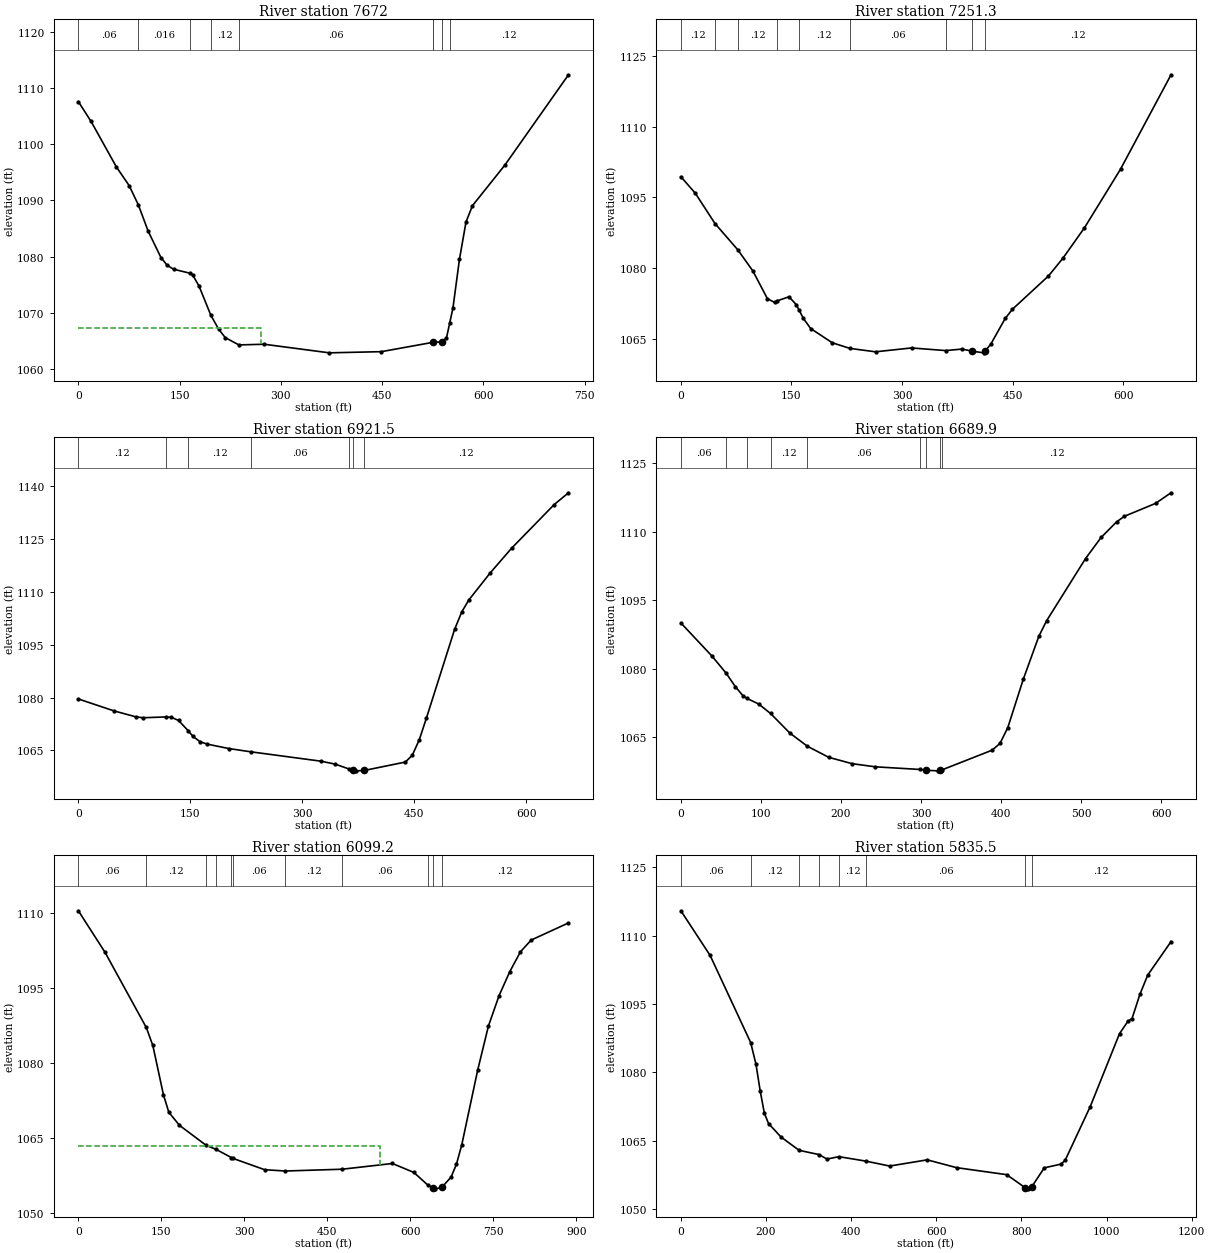
Type RM Length L Ch R = 1 ,7672    ,422,420.7,417.3
XS GIS Cut Line= 4
     1789695.811        244489.2     1789595.985      244352.481
     1789164.127      244311.249      1789049.11      244354.651
#Sta/Elev= 30
       0  1107.6    18.8 1104.08    56.4 1095.96    75.2 1092.66   88.981089.187
   103.4 1084.54   122.3 1079.85   131.7 1078.45   141.1 1077.76  164.711077.073
   169.3 1076.76   178.9 1074.72  196.351069.539   207.8  1067.1   217.5  1065.6
  237.69 1064.29   275.3 1064.41   371.7 1062.88   448.9 1063.09  524.661064.739
     526 1064.76  539.14 1064.84   545.3 1065.54     550 1068.16   554.9 1070.89
   564.5 1079.54   574.2 1086.17   583.8 1089.09   631.5 1096.26     726 1112.38
#Mann= 9 ,-1 , 0
       0     .06       0   88.98    .016       0  164.71     .08       0
  196.35     .12       0  237.69     .06       0  524.66     .12       0
     526    .045       0  539.14    .045       0     550     .12       0
#XS Ineff= 2 , 0
          270.79  1067.3
Permanent Ineff=
       F       F
Bank Sta=526,539.14
XS Rating Curve= 0 ,0
Exp/Cntr=0.3,0.1

Type RM Length L Ch R = 1 ,7251.3  ,317.8,329.8,333.2
XS GIS Cut Line= 2
     1789752.235      243990.068     1789088.173      243959.686
#Sta/Elev= 30
       0 1099.37    19.6 1095.86   46.211089.447    77.31083.841    97.8 1079.33
   117.3  1073.5   127.1  1072.7  130.33 1073.02   146.6  1073.9   156.4 1072.24
  159.92 1071.18   166.2 1069.29     176 1067.16   205.3 1064.14  229.331062.938
     264 1062.22   312.8 1063.04  359.071062.481   381.3  1062.8  395.32 1062.35
   410.6    1062  412.58 1062.36   420.4 1063.86   439.9  1069.3   449.7 1071.25
   498.6 1078.32   518.1 1082.07   547.4 1088.54   596.3 1100.98   664.8 1121.01
#Mann= 9 ,-1 , 0
       0     .12       0   46.21     .06       0    77.3     .12       0
  130.33    .016       0  159.92     .12       0  229.33     .06       0
  359.07     .12       0  395.32    .045       0  412.58     .12       0
Bank Sta=395.32,412.58
XS Rating Curve= 0 ,0
Exp/Cntr=0.3,0.1

Type RM Length L Ch R = 1 ,6921.5  ,237.5,231.5,225.5
XS GIS Cut Line= 4
     1789734.874       243705.78     1789457.096      243718.801
     1789268.294      243634.165     1789096.853      243627.655
#Sta/Elev= 30
       0 1079.64      48 1076.23    76.7 1074.58    86.3  1074.3  117.491074.533
   124.7 1074.42   134.2 1073.53  147.04 1070.64   153.4 1069.03     163  1067.5
   172.6 1066.81   201.4 1065.56  231.131064.621   325.1 1061.96   343.9 1061.13
  361.94  1059.8     368 1059.45   372.1 1059.22     383 1059.33     438 1061.71
   447.4 1063.66   456.8 1068.09   466.2 1074.16     504 1099.38   513.6 1104.36
   523.1 1107.76   551.7 1115.44   580.3 1122.44   637.5 1134.87   656.6 1138.21
#Mann= 7 ,-1 , 0
       0     .12       0  117.49    .016       0  147.04     .12       0
  231.13     .06       0  361.94     .12       0     368    .045       0
     383     .12       0
Bank Sta=368,383
XS Rating Curve= 0 ,0
Exp/Cntr=0.3,0.1

Type RM Length L Ch R = 1 ,6689.9  ,593.5,590.7,586.6
XS GIS Cut Line= 3
     1789695.811      243462.724     1789229.232      243456.214
     1789101.193      243525.658
#Sta/Elev= 30
       0 1089.98    38.9 1082.71    56.41079.001      68 1076.03    77.8 1073.97
   82.451073.452    97.2 1072.22     1121070.139   136.1 1065.85  157.981062.962
   184.7 1060.53   213.9 1059.14     243 1058.45  298.291057.877   306.6 1057.69
   320.8 1057.57  323.61 1057.66   326.3 1057.79   388.8  1062.1   398.6 1063.57
   408.3 1067.01   427.7 1077.63   447.2 1087.08   456.9 1090.48   505.5  1104.1
   524.9 1108.72   544.3 1112.14     554 1113.36   592.9 1116.19   612.3 1118.52
#Mann= 9 ,-1 , 0
       0     .06       0    56.4     .12       0   82.45    .016       0
     112     .12       0  157.98     .06       0  298.29     .12       0
   306.6    .045       0  323.61    .045       0   326.3     .12       0
Bank Sta=306.6,323.61
XS Rating Curve= 0 ,0
Exp/Cntr=0.3,0.1

Type RM Length L Ch R = 1 ,6099.2  ,234.3,263.7,288.1
XS GIS Cut Line= 4
     1789817.339      243195.797     1789493.989      243102.481
     1789383.311      242933.211     1789036.089      242933.211
#Sta/Elev= 30
       0 1110.52    48.1 1102.23  122.771087.176   134.6 1083.58   153.8 1073.71
   163.5 1070.23   182.7 1067.61  231.27 1063.58  248.831062.805  276.691061.146
  279.721060.984   336.6 1058.73   373.91058.465  476.861058.824   567.7 1059.97
   606.3 1058.19  631.321055.698   641.8 1055.02   644.9  1054.9   656.8 1055.17
   673.8 1057.26   683.5 1059.83   693.1 1063.72     722 1078.72   741.3 1087.48
   760.6 1093.57   779.9 1098.35   799.2 1102.32   818.5 1104.66     886 1108.09
#Mann= 11 ,-1 , 0
       0     .06       0  122.77     .12       0  231.27    .016       0
  248.83     .12       0  276.69    .016       0  279.72     .06       0
   373.9     .12       0  476.86     .06       0  631.32     .12       0
   641.8    .045       0   656.8     .12       0
#XS Ineff= 2 , 0
          545.92 1063.48
Permanent Ineff=
       F       F
Bank Sta=641.8,656.8
XS Rating Curve= 0 ,0
Exp/Cntr=0.3,0.1

Type RM Length L Ch R = 1 ,5835.5  ,95.8,92.4,93.2
XS GIS Cut Line= 4
     1789863.565      243168.587     1789529.892      243088.734
     1789174.423      242466.338     1789083.342      242475.446
#Sta/Elev= 30
       0 1115.46    68.6 1105.67   163.91086.551   176.4 1081.78   186.2 1075.98
     196 1071.07   205.9 1068.78   235.3 1065.82  277.771062.907   324.3 1061.98
   343.1 1060.99  371.311061.518  435.851060.518   490.4 1059.46   578.7 1060.82
   647.5 1059.11   765.3 1057.57   808.8 1054.71   814.4 1054.46   823.8 1054.86
   853.7 1059.07   892.9 1059.88   902.8 1060.74   961.7 1072.52  1030.4 1088.51
    1050  1091.2  1059.8 1091.82  1078.2  1097.1  1096.5 1101.33  1151.4  1108.7
#Mann= 8 ,-1 , 0
       0     .06       0   163.9     .12       0  277.77    .016       0
   324.3     .06       0  371.31     .12       0  435.85     .06       0
   808.8    .045       0   823.8     .12       0
Bank Sta=808.8,823.8
XS Rating Curve= 0 ,0
Exp/Cntr=0.3,0.1

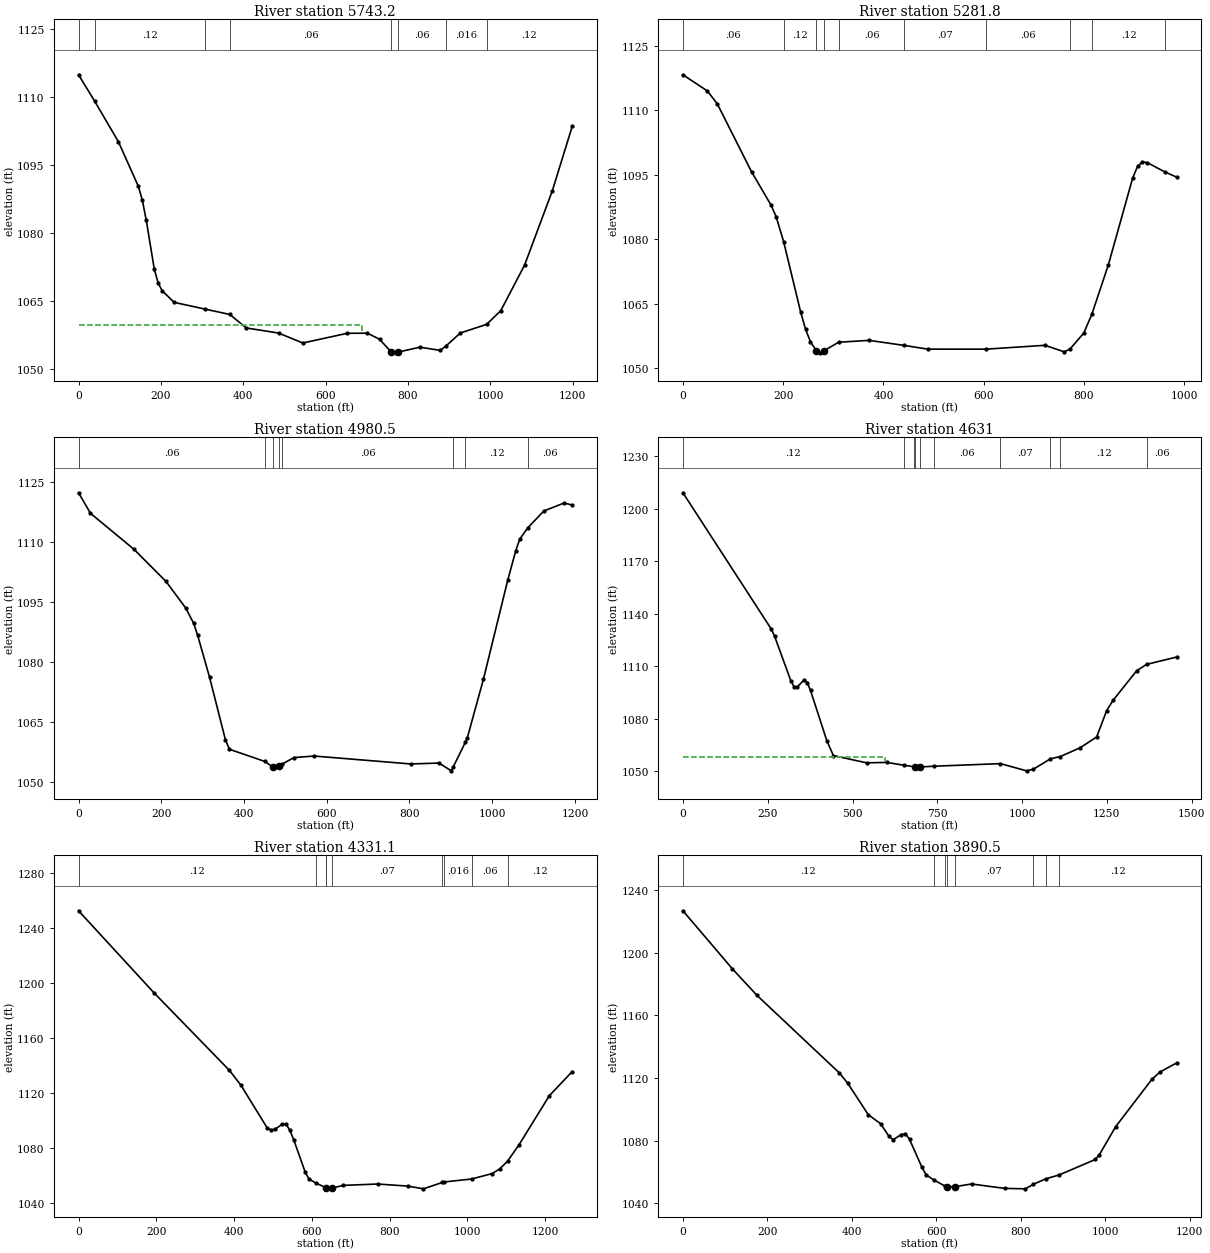
Type RM Length L Ch R = 1 ,5743.2  ,465.9,461.3,456.5
XS GIS Cut Line= 4
     1789873.363      243121.778     1789540.309      242989.775
     1789256.455      242385.609     1789084.791       242410.21
#Sta/Elev= 30
       0 1114.94   39.411109.088    96.8 1100.19   145.2 1090.37   154.9 1087.33
   164.6 1082.84     184 1072.11   193.6 1068.98   203.3 1067.32   232.4 1064.77
  307.48 1063.29  367.581062.106   407.3 1059.14   485.9 1058.01   544.8 1055.82
   652.8 1057.96   701.8 1057.98   731.3 1056.64  759.35 1053.85   770.6 1053.65
  775.53  1053.8   829.4  1054.9   878.5 1054.19  892.381055.144   927.6 1058.03
  991.411059.931  1025.8 1062.96  1083.6    1073    1151 1089.38  1199.2 1103.55
#Mann= 8 ,-1 , 0
       0     .06       0   39.41     .12       0  307.48    .016       0
  367.58     .06       0  759.35    .045       0  775.53     .06       0
  892.38    .016       0  991.41     .12       0
#XS Ineff= 2 , 0
          689.78  1059.7
Permanent Ineff=
       F       F
Bank Sta=759.35,775.53
XS Rating Curve= 0 ,0
Exp/Cntr=0.3,0.1

Type RM Length L Ch R = 1 ,5281.8  ,321.3,301.3,280.8
XS GIS Cut Line= 3
     1789947.548      242642.412     1789741.384      242368.974
     1789101.193      242316.891
#Sta/Elev= 30
       0 1118.27    48.9 1114.49    68.5 1111.52     137 1095.69   176.1  1087.9
   185.9 1085.28  200.851079.491   234.8 1063.11   244.6 1059.13   254.4 1056.18
   266.1 1054.15     274 1053.62  281.65 1054.13   310.61056.083   371.6 1056.52
  441.64 1055.34   488.4 1054.48  604.011054.475     722 1055.37   760.9 1053.85
  772.311054.519   799.8 1058.24  815.751062.604   848.5    1074   897.2 1094.27
   906.9 1096.97   916.6 1098.01   926.4 1097.84  962.591095.615   984.8 1094.48
#Mann= 10 ,-1 , 0
       0     .06       0  200.85     .12       0   266.1    .045       0
  281.65     .12       0   310.6     .06       0  441.64     .07       0
  604.01     .06       0  772.31    .016       0  815.75     .12       0
  962.59     .06       0
Bank Sta=266.1,281.65
XS Rating Curve= 0 ,0
Exp/Cntr=0.3,0.1

Type RM Length L Ch R = 1 ,4980.5  ,351.3,349.5,347.8
XS GIS Cut Line= 3
     1790175.412      242390.676     1789862.912      242184.513
      1789044.77       242147.62
#Sta/Elev= 30
       0 1122.22    28.8  1117.1   134.4 1108.05   211.2 1100.08   259.2  1093.4
   278.4 1089.56     288 1086.58   316.8 1076.07   355.2 1060.44   364.8  1058.1
  450.331055.057   469.9 1053.65   484.9 1053.81  492.641054.422   520.6 1056.02
   569.4 1056.41   803.4 1054.43   871.6 1054.66   900.9 1052.71  906.131053.761
  935.061059.829   939.9 1060.98   978.9 1075.65  1037.4  1100.3  1056.9 1107.72
  1066.6 1110.62 1085.691113.423  1125.1 1117.69  1173.8 1119.65  1193.4 1119.16
#Mann= 8 ,-1 , 0
       0     .06       0  450.33     .12       0   469.9    .045       0
   484.9     .12       0  492.64     .06       0  906.13    .016       0
  935.06     .12       0 1085.69     .06       0
Bank Sta=469.9,484.9
XS Rating Curve= 0 ,0
Exp/Cntr=0.3,0.1

Type RM Length L Ch R = 1 ,4631    ,307,299.9,292
XS GIS Cut Line= 4
     1790244.857      241446.665     1789960.568       241824.27
     1789272.634      241845.971     1789068.641      242058.645
#Sta/Elev= 30
       0 1209.17   260.4 1131.28   270.1 1127.24   318.3 1101.58     328 1098.21
   337.6 1098.26   356.9 1102.12   366.6 1100.63   376.2 1096.12   424.4 1067.34
   443.7 1058.91   541.5 1054.75   600.5    1055  651.191053.408  682.751052.478
     683 1052.47   698.8 1052.39  740.521052.827  936.341054.297  1013.4 1050.18
  1033.1 1051.08 1083.351057.042 1112.891058.367  1170.8 1063.34  1219.9 1069.52
  1249.3 1084.58    1269 1090.68  1337.8  1107.4 1366.951111.042  1455.6 1115.24
#Mann= 10 ,-1 , 0
       0     .12       0  651.19     .06       0  682.75     .12       0
     683    .045       0   698.8     .12       0  740.52     .06       0
  936.34     .07       0 1083.35    .016       0 1112.89     .12       0
 1366.95     .06       0
#XS Ineff= 2 , 0
          596.08 1058.24
Permanent Ineff=
       F       F
Bank Sta=683,698.8
XS Rating Curve= 0 ,0
Exp/Cntr=0.3,0.1

Type RM Length L Ch R = 1 ,4331.1  ,438.5,440.7,443.3
XS GIS Cut Line= 4
     1790175.412      241249.183     1789750.065       241520.45
     1789263.954      241704.912     1789025.239      241648.488
#Sta/Elev= 30
       0 1252.86     194 1193.19   388.1  1136.7   417.2  1126.1   485.1  1094.9
   494.8 1093.42   504.5 1093.77   524.1 1097.48   533.9 1097.54   543.7 1093.03
   553.5 1086.16     583 1062.63   592.8 1057.53  610.861054.696   635.4  1051.4
  637.44 1051.11   651.6 1051.06   681.1    1053   769.4    1054   847.8 1052.46
   887.1 1050.49  935.221055.104  940.281055.477 1010.851057.637  1063.7  1061.6
  1083.3 1064.96 1103.341070.569  1132.4  1082.3  1210.8 1118.24  1269.7 1135.84
#Mann= 9 ,-1 , 0
       0     .12       0  610.86     .07       0   635.4    .045       0
  637.44    .045       0   651.6     .07       0  935.22     .06       0
  940.28    .016       0 1010.85     .06       0 1103.34     .12       0
Bank Sta=637.44,651.6
XS Rating Curve= 0 ,0
Exp/Cntr=0.3,0.1

Type RM Length L Ch R = 1 ,3890.5  ,515.7,530.3,532.1
XS GIS Cut Line= 4
     1790060.395      241190.589     1789648.068      241114.634
     1789118.555      241253.523     1788990.516      241409.773
#Sta/Elev= 30
       0 1226.82     117 1189.74   175.5 1172.71   370.5 1123.17     390 1116.69
   438.8  1096.5   468.1 1090.73   487.7 1082.71   497.5  1080.5     517 1083.86
   526.8 1084.28   536.6 1080.69   565.9 1062.88   575.7 1058.08  594.251054.778
   621.1 1050.82   624.6 1050.52   644.1 1050.52   683.2 1052.25   761.4 1049.44
   810.3 1049.14  829.581052.033  859.981055.634  890.391057.994   976.3  1067.9
   985.9 1070.96  1024.4 1088.85    1111 1119.38  1130.2  1123.9  1168.7 1129.58
#Mann= 8 ,-1 , 0
       0     .12       0  594.25     .07       0   621.1    .045       0
   624.6    .045       0   644.1     .07       0  829.58     .06       0
  859.98    .016       0  890.39     .12       0
Bank Sta=624.6,644.1
XS Rating Curve= 0 ,0
Exp/Cntr=0.3,0.1

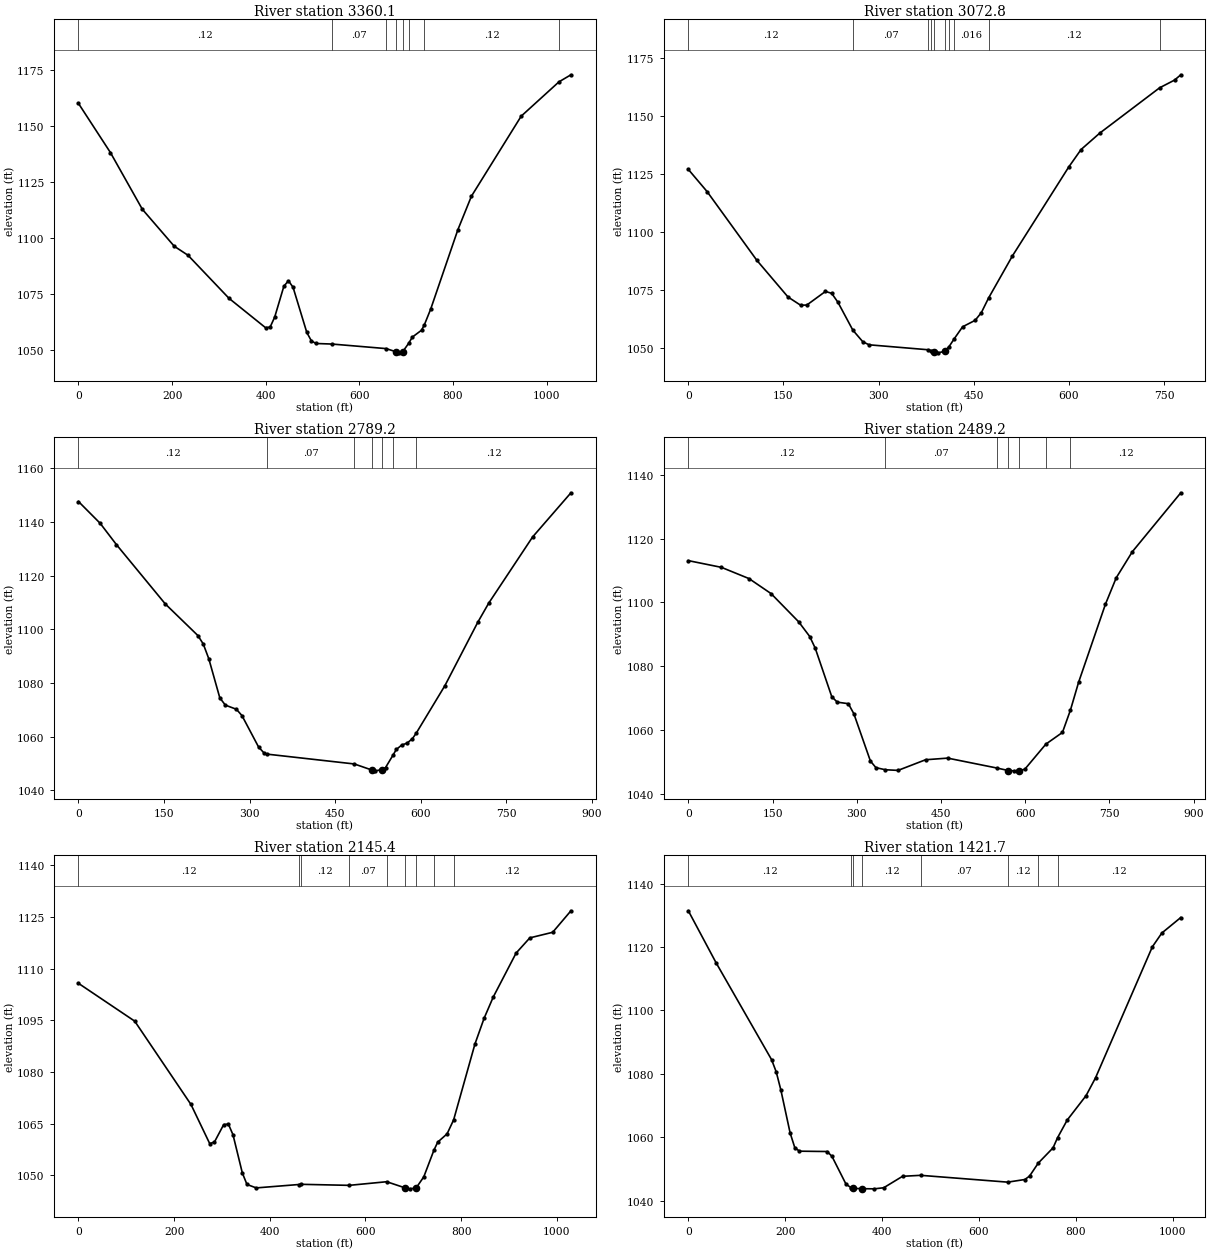
Type RM Length L Ch R = 1 ,3360.1  ,292.3,287.3,281.9
XS GIS Cut Line= 4
     1789715.343      240502.655     1789476.627      240810.815
     1789122.895       240891.11     1788825.586      240854.217
#Sta/Elev= 30
       0 1160.18    68.2 1138.28   136.4 1112.96   204.6 1096.46   233.9 1092.45
   321.6 1073.22   399.6 1060.12   409.4 1060.37   419.2 1064.85   438.8 1078.62
   448.6 1081.06   458.4 1078.16   487.8 1057.99   497.6 1054.23   507.4 1053.07
  541.571052.821  657.221050.792   677.7 1049.42   683.9  1048.9   692.7 1049.42
  705.231053.097   713.3 1055.93   732.9    1059  738.821061.344   752.5 1068.44
   810.5 1103.82   839.5 1118.79   945.8  1154.5 1026.491169.818  1052.1 1172.97
#Mann= 8 ,-1 , 0
       0     .12       0  541.57     .07       0  657.22     .12       0
   677.7    .045       0   692.7     .12       0  705.23    .016       0
  738.82     .12       0 1026.49    .016       0
Bank Sta=677.7,692.7
XS Rating Curve= 0 ,0
Exp/Cntr=0.3,0.1

Type RM Length L Ch R = 1 ,3072.8  ,285.7,283.6,281.5
XS GIS Cut Line= 2
     1789492.902      240425.621     1788793.974      240763.246
#Sta/Elev= 30
       0 1126.86    29.5 1117.34   108.1 1087.67   157.2 1071.88   176.9 1068.38
   186.7 1068.42   216.2 1074.31     226 1073.47   235.8 1069.64  259.321057.622
   275.1  1052.6   284.9 1051.31  378.451049.167   383.2 1048.76  386.45  1048.4
     393 1047.85  403.78 1048.46     4111050.556   419.41054.025   432.3 1059.07
     452 1061.84   461.8 1065.14  473.171071.433   510.9 1089.63   599.4 1127.82
     619 1135.42   648.5 1142.49  742.821162.009   766.4 1165.34   776.2 1167.62
#Mann= 10 ,-1 , 0
       0     .12       0  259.32     .07       0  378.45     .06       0
   383.2    .045       0  386.45    .045       0  403.78     .06       0
     411     .12       0   419.4    .016       0  473.17     .12       0
  742.82    .016       0
Bank Sta=386.45,403.78
XS Rating Curve= 0 ,0
Exp/Cntr=0.3,0.1

Type RM Length L Ch R = 1 ,2789.2  ,297,300,299.1
XS GIS Cut Line= 5
     1789444.075      240190.155     1789226.621      240213.302
      1788961.86      240374.489     1788864.272      240432.579
     1788725.759      240604.651
#Sta/Elev= 30
       0 1147.62      38  1139.5    66.6 1131.53   152.1 1109.45   209.2 1097.67
   218.7 1094.51   228.4 1089.01   247.7 1074.43   257.4 1071.72   276.8 1070.17
   286.5 1067.82   315.6 1056.12   325.2 1053.87  330.181053.454  483.391049.785
  514.04 1047.53     519 1047.22  532.18 1047.63   538.1 1048.42  551.571053.187
     557 1055.18   566.5 1056.83     576 1057.56   585.4 1059.24  592.411061.432
   642.2 1078.98   699.8  1102.6     719 1109.74   795.9 1134.41   863.1 1150.88
#Mann= 7 ,-1 , 0
       0     .12       0  330.18     .07       0  483.39     .12       0
  514.04    .045       0  532.18     .12       0  551.57    .016       0
  592.41     .12       0
Bank Sta=514.04,532.18
XS Rating Curve= 0 ,0
Exp/Cntr=0.3,0.1

Type RM Length L Ch R = 1 ,2489.2  ,341.4,343.8,349.6
XS GIS Cut Line= 3
     1789335.537      239885.189     1788796.574       240124.76
     1788554.619      240279.962
#Sta/Elev= 30
       0 1113.11      59    1111   108.1 1107.48   147.4 1102.77   196.6 1093.92
   216.3 1089.31   226.1 1085.64   255.6 1070.41   265.4 1068.72   285.1 1068.24
   294.9 1065.08   324.4 1050.25   334.2 1048.18   351.11047.519   373.6 1047.32
   422.7 1050.66     462 1051.17  550.351048.038   570.2 1047.27     580 1047.18
   589.8 1047.22   599.4 1047.68     6371055.564   666.5 1059.23  680.741066.247
   695.2 1074.93   743.1 1099.46   762.3 1107.73     791 1115.91   877.3 1134.39
#Mann= 7 ,-1 , 0
       0     .12       0   351.1     .07       0  550.35     .12       0
   570.2    .045       0   589.8     .12       0     637    .016       0
  680.74     .12       0
Bank Sta=570.2,589.8
XS Rating Curve= 0 ,0
Exp/Cntr=0.3,0.1

Type RM Length L Ch R = 1 ,2145.4  ,725.8,723.7,717.9
XS GIS Cut Line= 4
     1789266.124      239819.061     1788994.857      239734.426
     1788478.364      239908.037      1788424.11      240101.179
#Sta/Elev= 30
       0 1105.72   117.6 1094.75   235.2 1070.58   274.4 1059.23   284.2 1059.67
   303.6 1064.74   313.4  1064.9   323.1 1061.79   342.6 1050.72   352.3 1047.38
   371.7 1046.38   460.21047.359  466.07 1047.42  565.971047.122  644.461048.174
   683.1 1046.38   692.8 1046.11     706 1046.37     722 1049.59  743.251057.342
   751.2 1059.67   770.7 1062.06   784.41066.119     829 1088.14   848.2 1095.62
   867.3 1101.77     915  1114.5   943.7 1118.91   991.5 1120.53  1029.7 1126.77
#Mann= 9 ,-1 , 0
       0     .12       0   460.2     .06       0  466.07     .12       0
  565.97     .07       0  644.46     .06       0   683.1    .045       0
     706     .12       0  743.25    .016       0   784.4     .12       0
Bank Sta=683.1,706
XS Rating Curve= 0 ,0
Exp/Cntr=0.3,0.1

Type RM Length L Ch R = 1 ,1421.7  ,588.3,631.8,630.7
XS GIS Cut Line= 4
     1788921.812      239081.102     1788715.222      239265.817
     1788232.583      239494.984     1788027.489      239505.592
#Sta/Elev= 30
       0 1131.42    57.3 1115.04     172 1084.47   181.6 1080.59   191.1 1074.91
   210.2 1061.39   219.8 1056.78   229.4 1055.65   286.8 1055.54   296.6 1054.01
   325.7 1045.22   336.9 1044.07  340.16 1043.92  358.99 1043.83     384 1043.78
   403.4 1044.12   442.3 1047.73  479.831048.039  659.47 1045.89   694.8 1046.72
   704.6 1047.81  722.611051.907   753.1 1056.71  762.271059.868   782.3 1065.46
   821.2 1073.15   840.8 1078.78   958.1 1120.07   977.7 1124.41  1016.8  1129.3
#Mann= 8 ,-1 , 0
       0     .12       0   336.9    .045       0  340.16    .045       0
  358.99     .12       0  479.83     .07       0  659.47     .12       0
  722.61    .016       0  762.27     .12       0
Bank Sta=340.16,358.99
XS Rating Curve= 0 ,0
Exp/Cntr=0.3,0.1

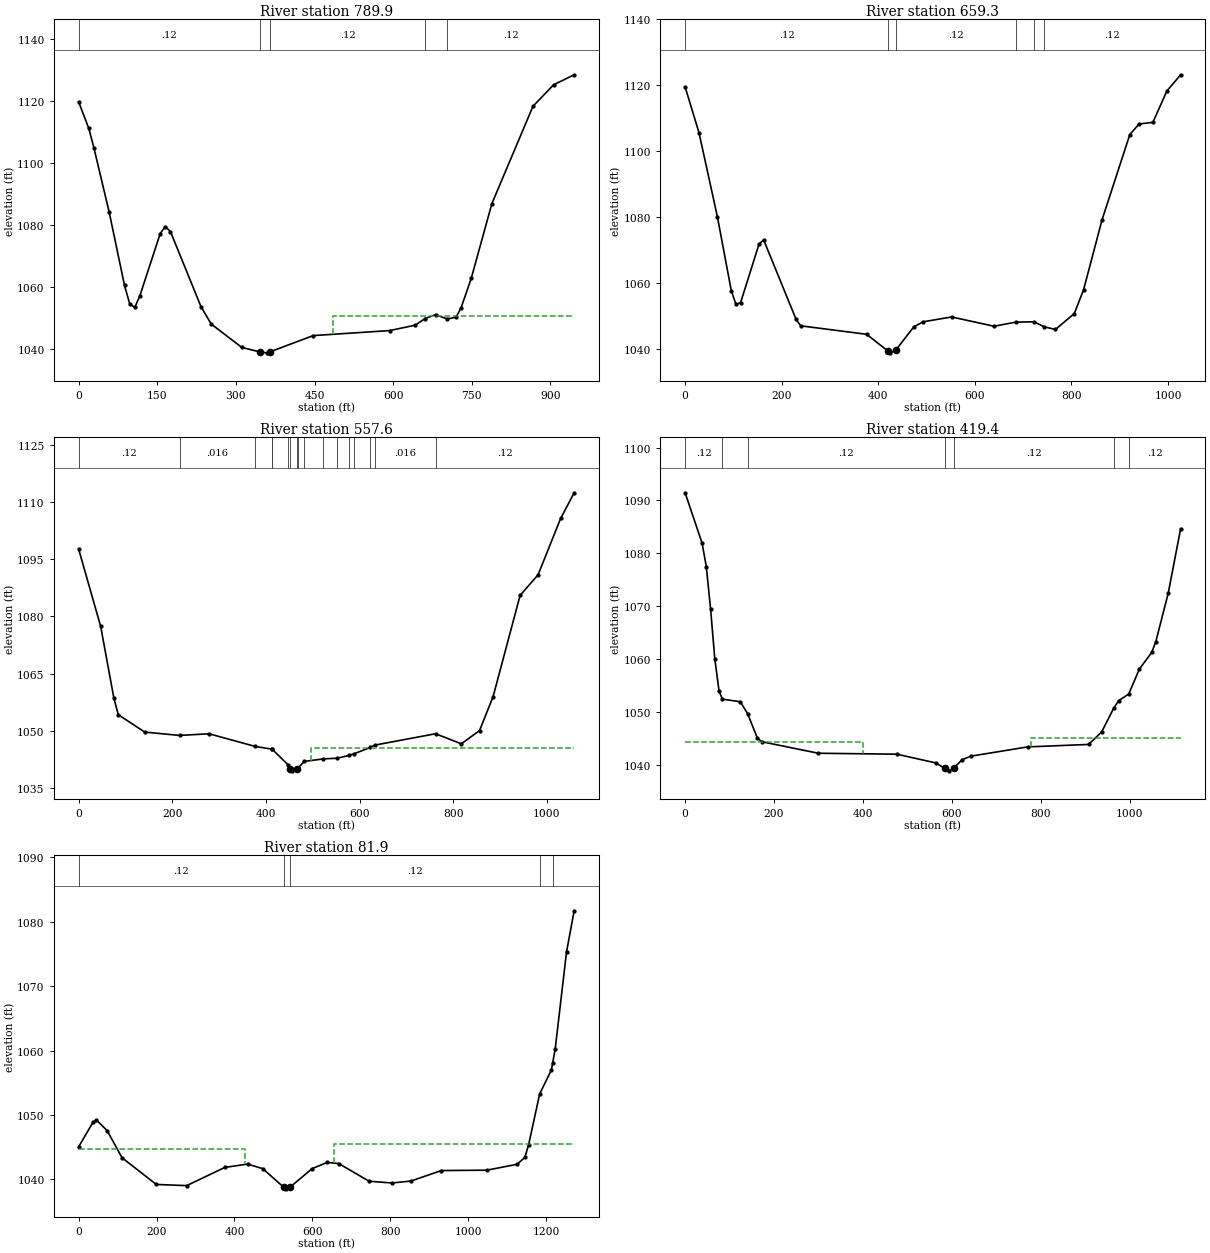
Type RM Length L Ch R = 1 ,789.9   ,169.8,130.6,130.8
XS GIS Cut Line= 3
     1788654.145      238729.651     1788016.124      239102.915
     1787933.659      239291.717
#Sta/Elev= 30
       0 1119.72    19.4 1111.13    29.2 1104.81    58.4 1083.98    87.5 1060.43
    97.3 1054.55     107 1053.32   116.7 1057.03   155.6 1077.16   165.3 1079.45
   175.1 1077.82   233.4 1053.57   252.9 1047.95   311.2 1040.41  345.96 1038.93
   359.9 1038.65     365 1038.97   447.4 1044.22   593.3 1045.84   641.9 1047.58
  661.021049.734   680.8 1050.97  702.621049.617   719.7  1050.1   729.5  1053.2
     749 1062.77   788.2 1086.83   866.7  1118.3     906 1125.22   945.2 1128.45
#Mann= 5 ,-1 , 0
       0     .12       0  345.96    .045       0     365     .12       0
  661.02    .016       0  702.62     .12       0
#XS Ineff= 2 , 0
                          485.04         1050.41
Permanent Ineff=
       F       F
Bank Sta=345.96,365
XS Rating Curve= 0 ,0
Exp/Cntr=0.3,0.1

Type RM Length L Ch R = 1 ,659.3   ,103.1,101.7,99.9
XS GIS Cut Line= 4
     1788643.899      238698.972     1788397.816      238736.122
     1787920.083      239022.761     1787830.646      239223.968
#Sta/Elev= 30
       0 1119.54    28.7 1105.68      67 1080.03    95.7 1057.67   105.3 1053.55
   114.9 1054.05   153.2 1071.89   162.7 1073.09   229.7 1049.05   239.3 1047.03
   375.9 1044.46   420.8 1039.29   424.8 1038.83   435.8 1039.55   473.7 1046.74
   493.2 1048.25   551.9 1049.72   639.8  1046.9  685.191048.154  722.411048.255
  743.72 1046.73   766.9 1045.92     806 1050.75   825.2 1057.97   863.4 1079.18
   920.9 1105.05     940 1108.27   968.8 1108.79   997.5 1118.24  1026.2 1123.21
#Mann= 6 ,-1 , 0
       0     .12       0   420.8    .045       0   435.8     .12       0
  685.19    .016       0  722.41     .08       0  743.72     .12       0
Bank Sta=420.8,435.8
XS Rating Curve= 0 ,0
Exp/Cntr=0.3,0.1

Type RM Length L Ch R = 1 ,557.6   ,138.7,138.2,137.3
XS GIS Cut Line= 4
     1788572.474      238587.879     1788431.241      238589.076
     1787851.814      238974.492     1787782.352      239184.659
#Sta/Elev= 30
       0 1097.64    47.1 1077.41    75.3 1058.62    84.7  1054.3   141.2 1049.74
  215.67 1048.87   278.5  1049.3  377.111045.993   412.21045.275  413.561045.246
  447.291041.183   452.1 1040.18   454.9  1039.6   467.1 1040.14  468.271040.328
  482.381042.078  522.971042.729  552.561042.905  577.681043.629  587.651044.039
  622.751045.712  632.381046.325  762.371049.307   817.5 1046.67   856.4 1050.15
   885.3 1059.02     943 1085.52   981.5 1090.93  1029.6 1105.67  1058.5 1112.38
#Mann= 17 ,-1 , 0
       0     .12       0  215.67    .016       0  377.11     .08       0
   412.2     .12       0  413.56     .08       0  447.29     .12       0
   452.1    .045       0   467.1     .12       0  468.27     .08       0
  482.38     .12       0  522.97     .08       0  552.56     .12       0
  577.68    .016       0  587.65     .08       0  622.75     .12       0
  632.38    .016       0  762.37     .12       0
#XS Ineff= 2 , 0
                          496.59         1045.51
Permanent Ineff=
       F       F
Bank Sta=452.1,467.1
XS Rating Curve= 0 ,0
Exp/Cntr=0.3,0.1

Type RM Length L Ch R = 1 ,419.4   ,334.4,337.5,337.6
XS GIS Cut Line= 4
     1788560.829      238493.106     1788400.239      238469.235
     1787749.197      238924.964     1787714.475      239079.044
#Sta/Elev= 30
       0 1091.44    38.2 1081.92    47.8 1077.43    57.3 1069.47    66.8 1060.06
    76.4  1053.9   83.991052.374   124.2 1051.89   140.61049.646   162.4 1045.06
   172.2 1044.33   299.7 1042.14   476.3 1041.96   564.6  1040.3   584.2 1039.26
     594 1038.81   604.1 1039.31   623.5 1040.93   643.1 1041.59   770.6 1043.34
     908 1043.81   937.4 1046.19  964.72 1050.73   975.6  1052.1  998.121053.339
  1022.1 1058.07    1050 1061.23  1059.2 1063.28  1087.1 1072.44    1115 1084.64
#Mann= 7 ,-1 , 0
       0     .12       0   83.99    .016       0   140.6     .12       0
   584.2    .045       0   604.1     .12       0  964.72    .016       0
  998.12     .12       0
#XS Ineff= 2 , 0
             400 1044.31  778.95         1045.02
Permanent Ineff=
       F       F
Bank Sta=584.2,604.1
XS Rating Curve= 0 ,0
Exp/Cntr=0.3,0.1

Type RM Length L Ch R = 1 ,81.9    ,85.7,81.9,77.9
XS GIS Cut Line= 4
     1788388.185       238279.98     1788311.576      238249.758
     1787592.826      238701.147     1787584.159      239042.062
#Sta/Elev= 30
       0 1045.05    36.6 1048.83    45.8 1049.22    73.2 1047.56   111.6 1043.34
   199.4  1039.2   277.5 1039.02     375 1041.84   433.6 1042.37   472.6 1041.66
   526.2 1038.78   531.1 1038.52  542.49 1038.77   599.4 1041.66   638.4 1042.63
   667.7 1042.45   745.7  1039.7   804.3 1039.43     853 1039.73   931.1 1041.36
    1048 1041.42    1126 1042.34  1145.4 1043.41  1155.2 1045.38 1183.651053.288
  1213.6 1056.98 1217.021058.125  1223.4 1060.26  1252.6 1075.38  1272.1 1081.72
#Mann= 5 ,-1 , 0
       0     .12       0   526.2    .045       0  542.49     .12       0
 1183.65    .016       0 1217.02     .12       0
#XS Ineff= 2 , 0
          427.66  1044.7  654.49         1045.51
Permanent Ineff=
       F       F
Bank Sta=526.2,542.49
XS Rating Curve= 0 ,0
Exp/Cntr=0.3,0.1

Chan Stop Cuts=-1
Use User Specified Reach Order=0
Composite Channel Slope=5